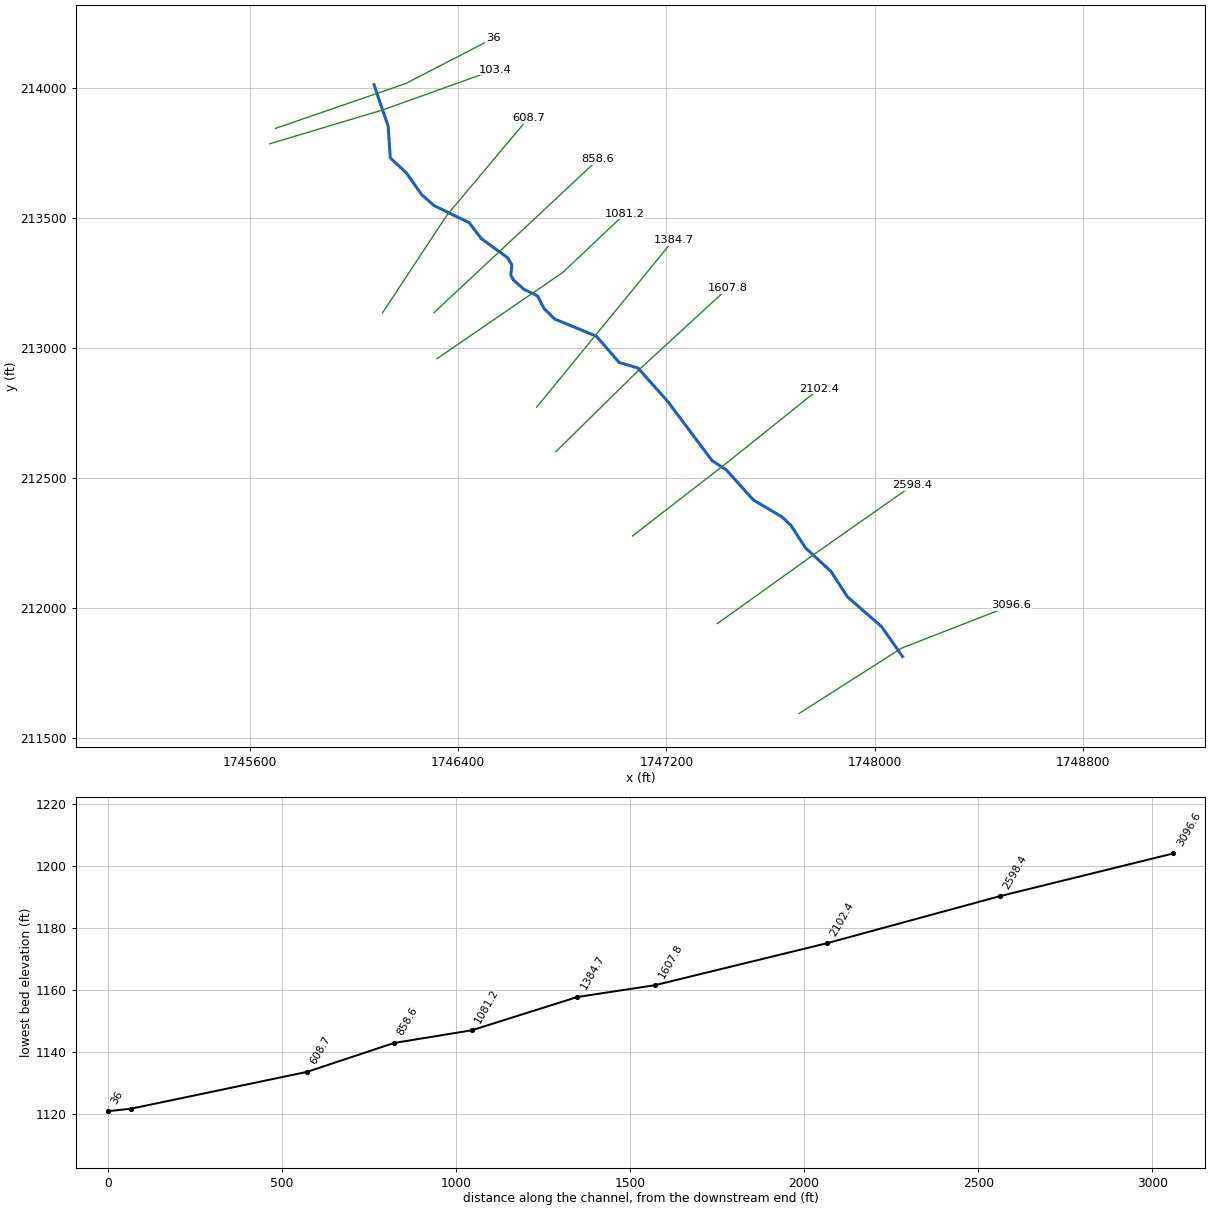
--- BigBr1.prj (project) ---

Proj Title=BigBr1
Current Plan=p01
Default Exp/Contr=0,0
English Units
Geom File=g01
Flow File=f01
Plan File=p01
BEGIN DESCRIPTION:
END DESCRIPTION:
DSS Export Rating Curves= 0
DSS Export Rating Curve Sorted= 0
DSS Export Volume Flow Curves= 0
DXF OffsetX= 0
DXF OffsetY= 0
DXF ScaleX= 0
DXF ScaleY= 0

--- BigBr1.p01 (plan) ---

Plan Title=Floodplain
Program Version=4.00
Geom File=g01
Flow File=f01
K Sum by GR=0
Std Step Tol=0.01
Critical Tol=0.01
Num of Std Step Trials=20
Max Error Tol=0.3
Flow Tol Ratio=0.001
Split Flow NTrial=30
Split Flow Tol=0.02
Split Flow Ratio=0.02
Log Output Level=0
Friction Slope Method=1
Unsteady Friction Slope Method=2
Unsteady Bridges Friction Slope Method=1
Global Log Level=0
CheckData=False
Run HTab=0
Run UNet=0
Run PostProcess=0
UNET Theta=0
UNET Theta Warmup=0
UNET ZTol=0
UNET ZSATol=0
UNET MxIter=0
UNET MaxInSteps=0
UNET DtIC=0
UNET DtMin=0
UNET MaxCRTS=0
UNET WFStab=0
UNET SFStab=0
UNET WFX=0
UNET SFX=0
UNET DSS MLevel=0
UNET DZMax Abort=0
UNET Convert EG Bridges=0
UNET Use Existing IB Tables=0
UNET Froude Limit=0
UNET Froude Power=0
Write IC File=0
Echo Input=False
Echo Output=False
Write Detailed=0

--- BigBr1.f01 (steady flow) ---

Flow Title=NFF Regression Equation
Program Version=4.00
Number of Profiles=1
Profile Names=P100yr
River Rch & RM=BigBr1,Main      ,3096.6
622.3019
River Rch & RM=BigBr1,Main      ,1081.2
667.5490
River Rch & RM=BigBr1,Main      ,103.4
728.6004
River Rch & RM=BigBr1,Main      ,103.4
735.1520
Boundary for River Rch & Prof#=BigBr1,Main      ,1
Up Type=0
Dn Type=3
Dn Slope=0.016057

--- BigBr1.g01 (geometry) ---

Geom Title=USGS 10m DEM
Program Version=4.00

River Reach=BigBr1          ,Main
Reach XY= 30
      1748107.23      211812.417     1748025.897      211928.135
     1747894.851      212042.759     1747832.808      212139.304
     1747734.245      212230.836     1747678.244      212317.479
     1747643.376      212350.234     1747534.545      212414.687
      1747429.94      212530.915     1747374.996       212566.84
     1747206.819      212792.315     1747090.766      212922.919
     1747018.916      212944.052     1746930.841      213045.503
     1746771.005      213111.336     1746730.607      213151.235
     1746705.136      213200.329     1746652.271      213226.168
      1746612.12      213262.093      1746602.61      213280.055
     1746606.836       213319.15     1746590.987      213346.622
     1746488.495      213421.642     1746443.061      213481.869
     1746308.871      213547.379     1746261.323      213588.587
     1746201.096      213674.173     1746139.812       213731.23
      1746131.65      213852.852     1746077.213      214013.329

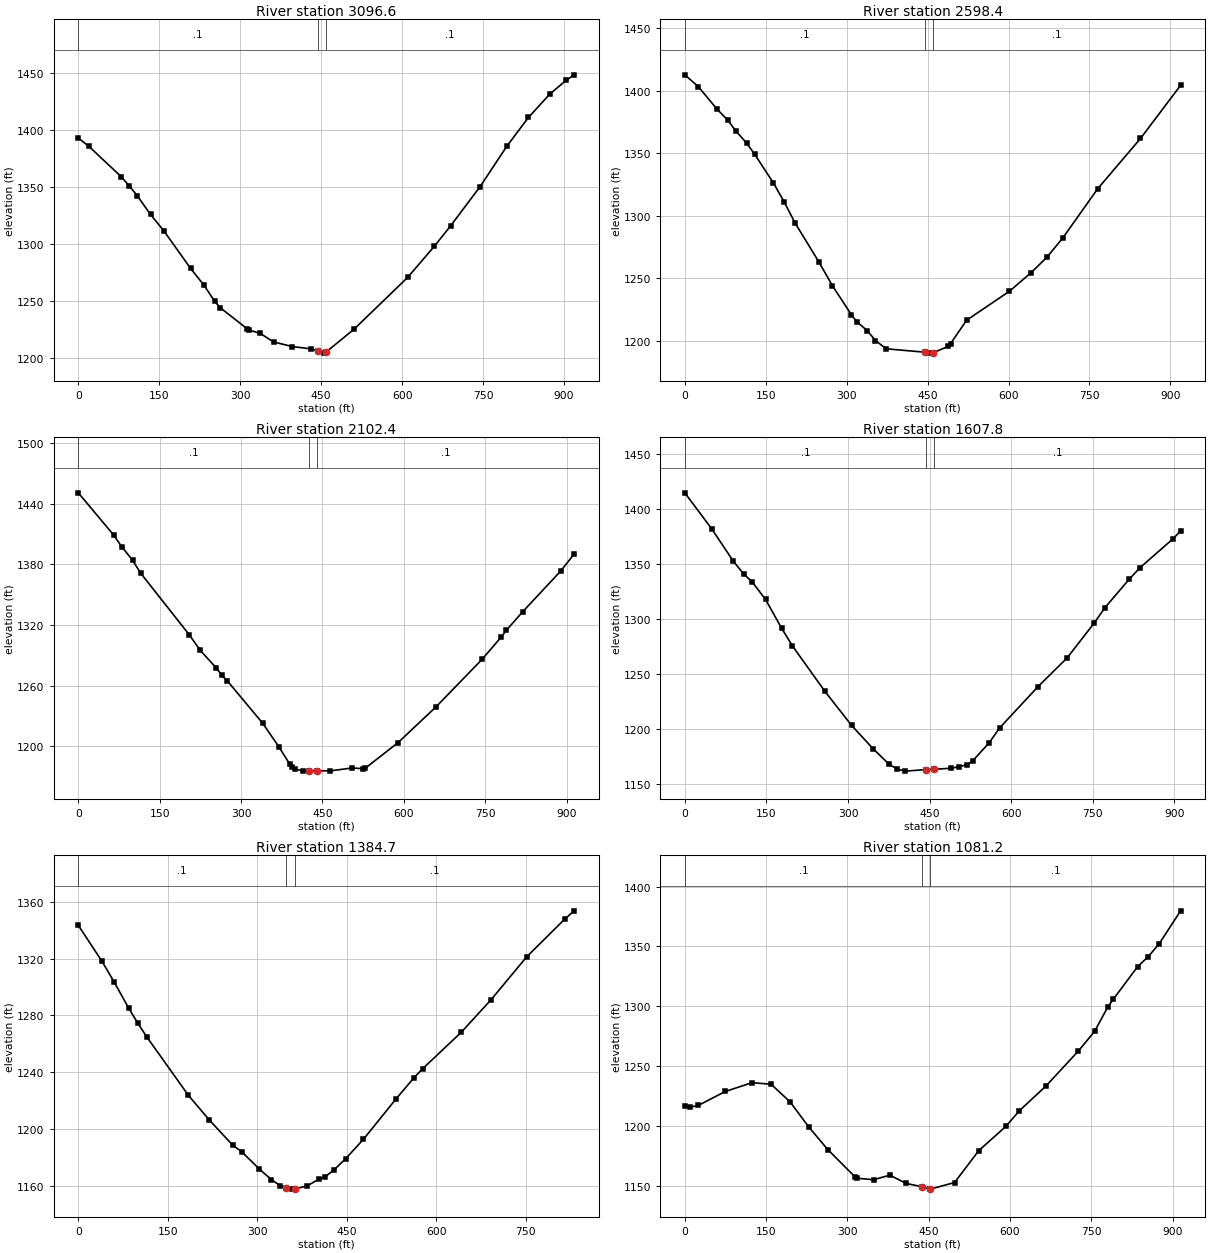
Type RM Length L Ch R = 1 ,3096.6  ,497,498.3,501
XS GIS Cut Line= 3
     1747710.453      211593.591     1748102.986      211844.362
     1748525.027      212009.213
#Sta/Elev= 30
       0 1392.74    19.8 1385.35    79.3 1358.89    94.2 1350.85     109 1342.24
   133.8 1325.68   158.6 1311.25   208.1 1278.37   232.9 1263.64   252.7 1249.54
   262.6 1244.08   312.2 1225.67   317.1  1224.2     337 1221.46   361.7 1213.94
   396.4 1209.86   431.1 1207.84   444.1    1206   455.9  1204.1   459.1 1205.07
   510.6 1224.92   610.2 1270.44     660 1297.93   689.9 1315.69   744.6 1350.15
   794.4 1385.72   834.2 1410.78   874.1 1431.48     904  1443.3   918.9 1448.17
#Mann= 3 , 0 , 0
       0      .1       0   444.1    .045       0   459.1      .1       0
Bank Sta=444.1,459.1
XS Rating Curve= 0 ,0
Exp/Cntr=0.3,0.1

Type RM Length L Ch R = 1 ,2598.4  ,495.2,496,496.8
XS GIS Cut Line= 3
     1747396.039       211939.32     1747764.187      212203.131
     1748145.274      212471.297
#Sta/Elev= 30
       0 1412.79    24.9  1403.4    59.7 1385.37    79.6 1376.53    94.6 1367.95
   114.5 1358.21   129.4 1349.34   164.2 1326.41   184.2 1311.18   204.1 1294.56
   248.8 1262.99   273.7 1244.16   308.6  1221.1   318.5 1215.59   338.4 1208.14
   353.4 1200.38   373.3 1193.78   445.1 1191.07   452.9 1190.33   460.1 1190.58
   487.6 1195.64   492.6 1197.96   522.3 1216.64   601.6 1239.77   641.3 1254.46
     671 1266.91   700.8 1282.55   765.2 1321.72   844.5  1361.9   918.9 1404.42
#Mann= 3 , 0 , 0
       0      .1       0   445.1    .045       0   460.1      .1       0
Bank Sta=445.1,460.1
XS Rating Curve= 0 ,0
Exp/Cntr=0.3,0.1

Type RM Length L Ch R = 1 ,2102.4  ,491.9,494.6,496.8
XS GIS Cut Line= 3
     1747070.061      212276.426     1747429.114      212555.051
     1747787.333      212842.968
#Sta/Elev= 30
       0 1450.96    64.9 1409.26    79.9 1397.64    99.9 1384.22   114.9 1371.36
   204.8 1310.12   224.7 1294.88   254.7  1277.2   264.7 1269.96   274.7 1264.59
   339.6 1222.85   369.6  1199.4   389.6 1182.26   394.6    1179   399.5 1177.34
   414.5 1175.19   425.4 1175.74   440.4  1175.6   464.5 1175.45   504.4 1178.29
   524.4 1177.66   529.4 1178.23   589.4 1203.43   659.3  1238.8   744.2 1285.87
   779.2 1307.78   789.2  1314.8   819.2  1333.1   889.1 1373.35   914.1 1390.35
#Mann= 3 , 0 , 0
       0      .1       0   425.4    .045       0   440.4      .1       0
Bank Sta=425.4,440.4
XS Rating Curve= 0 ,0
Exp/Cntr=0.3,0.1

Type RM Length L Ch R = 1 ,1607.8  ,231.8,223.1,225.8
XS GIS Cut Line= 3
     1746775.482      212600.487     1747099.356      212920.084
        1747435.      213229.115
#Sta/Elev= 30
       0 1414.83    49.5 1382.04      89 1352.77   108.8 1340.63   123.6 1333.95
   148.4 1317.82     178 1291.61   197.8 1275.62   257.2 1234.43   306.6 1203.23
   346.2 1181.96   375.9 1167.72   390.7 1163.42   405.6 1161.65   443.4 1163.06
   458.4 1163.33   489.7  1164.3   504.6 1165.74   519.5 1167.62   529.4 1171.13
   559.2  1187.3     579 1201.15   648.4 1238.11     703 1264.84   752.6 1296.51
   772.4 1310.48     817 1336.36   836.9 1346.85   896.4  1372.6   911.3  1380.1
#Mann= 3 , 0 , 0
       0      .1       0   443.4    .045       0   458.4      .1       0
Bank Sta=443.4,458.4
XS Rating Curve= 0 ,0
Exp/Cntr=0.3,0.1

Type RM Length L Ch R = 1 ,1384.7  ,310.9,303.5,296.4
XS GIS Cut Line= 2
     1746701.789      212771.892      1747227.42      213415.451
#Sta/Elev= 30
       0 1343.33    39.8 1317.96    59.7 1303.77    84.6 1284.95    99.5 1274.68
   114.4 1265.09   184.1 1223.99   218.9 1206.74   258.7 1188.73   273.7 1184.18
   303.5 1171.91   323.4 1164.56   338.4 1160.27   347.8 1158.56   358.2 1157.84
   362.8 1158.01   383.1 1160.03     403 1164.82     413 1166.41   427.9 1171.11
   447.8 1179.17   477.7 1192.84   532.4 1221.29   562.2 1236.04   577.2 1242.59
   641.9 1268.23   691.6 1291.04   751.3 1321.19     816  1348.1   830.9 1353.57
#Mann= 3 , 0 , 0
       0      .1       0   347.8    .045       0   362.8      .1       0
Bank Sta=347.8,362.8
XS Rating Curve= 0 ,0
Exp/Cntr=0.3,0.1

Type RM Length L Ch R = 1 ,1081.2  ,218,222.6,227.3
XS GIS Cut Line= 3
     1746319.074      212958.619     1746803.057      213291.252
     1747040.829      213516.505
#Sta/Elev= 30
       0 1216.51      10 1215.73    24.9 1217.08    74.6 1228.73   124.4 1236.13
   159.3 1234.77   194.1 1220.12   228.9 1198.95   263.8 1180.21   313.5 1157.59
   318.5 1156.22   348.4 1154.95   378.2 1158.82   408.1 1151.92   437.3 1149.14
   452.3 1147.12   452.9 1147.11   497.7 1152.61   542.5 1179.36   592.2 1199.49
     617  1212.5   666.7 1233.48   726.2 1262.59     756 1278.94   780.8 1299.64
   790.7 1305.92   835.4 1333.06   855.2 1341.54   875.1 1352.14   914.8 1379.76
#Mann= 3 , 0 , 0
       0      .1       0   437.3    .045       0   452.3      .1       0
Bank Sta=437.3,452.3
XS Rating Curve= 0 ,0
Exp/Cntr=0.3,0.1

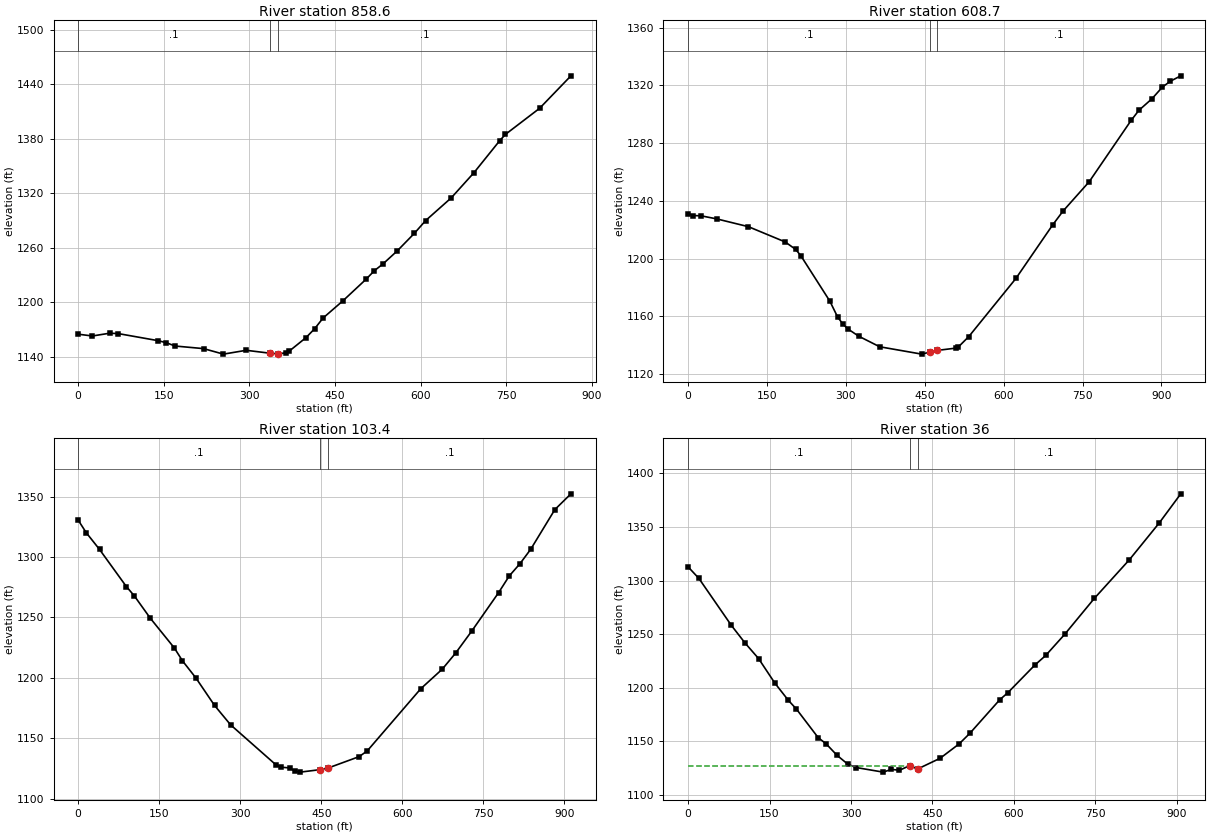
Type RM Length L Ch R = 1 ,858.6   ,247,249.9,252
XS GIS Cut Line= 2
     1746307.567      213135.789     1746937.649      213725.438
#Sta/Elev= 30
       0 1164.97    24.9    1163    54.9 1166.02    69.8 1165.67   139.7 1157.88
   154.6 1155.55   169.6 1151.96   219.5 1149.11   254.4 1143.04   294.3 1147.25
   335.2  1144.1   350.2  1143.3   364.1 1144.54   369.1 1146.08     399  1161.2
     414  1170.9     429  1182.8   463.9 1201.82   503.8 1225.19   518.8 1234.84
   533.7  1242.2   558.7 1256.54   588.6  1275.8   608.6 1289.99   653.4 1314.95
   693.4  1342.8   738.2 1377.79   748.2  1384.7   808.1 1413.43     863 1449.16
#Mann= 3 , 0 , 0
       0      .1       0   335.2    .045       0   350.2      .1       0
Bank Sta=335.2,350.2
XS Rating Curve= 0 ,0
Exp/Cntr=0.3,0.1

Type RM Length L Ch R = 1 ,608.7   ,518.9,505.2,493.6
XS GIS Cut Line= 3
     1746109.878      213135.035     1746356.795       213510.35
     1746669.759      213884.202
#Sta/Elev= 30
       0 1231.05      10 1229.78      25 1229.59    54.9 1227.44   114.8 1222.07
   184.7 1211.49   204.7 1206.31   214.6 1201.88   269.6 1170.48   284.5 1159.38
   294.5 1154.55   304.5 1151.05   324.5 1146.16   364.4 1138.83   444.3 1133.73
   459.2 1135.08   474.2 1136.32     509 1137.89   513.9  1138.7   533.8  1145.9
   623.4  1186.2     693 1223.17   712.9 1232.86   762.7 1253.23   842.3 1295.68
   857.2 1302.72   882.1 1310.77     902 1318.87   916.9 1322.87   936.8 1326.63
#Mann= 3 , 0 , 0
       0      .1       0   459.2    .045       0   474.2      .1       0
Bank Sta=459.2,474.2
XS Rating Curve= 0 ,0
Exp/Cntr=0.3,0.1

Type RM Length L Ch R = 1 ,103.4   ,66.5,67.4,67.1
XS GIS Cut Line= 3
     1745676.725       213785.69     1746113.005      213916.724
     1746542.778      214071.216
#Sta/Elev= 30
       0 1330.53    14.8 1320.19    39.6  1306.2    89.1 1275.56     104 1267.75
   133.7 1249.19   178.2 1224.55   193.1 1213.99   217.9 1199.86   252.5 1177.06
   282.2 1161.01   366.4 1127.79   376.3 1125.93   391.2 1125.36   401.1 1122.76
     411 1121.87     448 1123.92     463 1125.33   520.1  1134.7     535 1139.39
   634.2 1190.92     674 1207.13   698.8 1220.47   728.6 1238.67   778.2 1270.41
   798.1 1284.36   817.9 1294.48   837.8 1306.43   882.4 1339.24   912.2 1352.29
#Mann= 3 , 0 , 0
       0      .1       0     448    .045       0     463      .1       0
Bank Sta=448,463
XS Rating Curve= 0 ,0
Exp/Cntr=0.3,0.1

Type RM Length L Ch R = 1 ,36      ,31.3,36,40.7
XS GIS Cut Line= 3
     1745699.438      213845.073     1746199.443      214017.782
     1746535.266      214191.557
#Sta/Elev= 30
       0 1312.85      20 1301.99    79.8  1258.1   104.8 1241.76   129.8 1227.16
   159.7  1204.3   184.6 1188.16   199.6 1179.92   239.5 1153.34   254.5 1147.35
   274.5 1136.66   294.4 1128.38   309.4 1125.35   359.3 1121.05   374.3 1123.61
   389.3  1122.8   407.8 1127.07   422.8    1124   464.1    1134     499 1147.38
     519 1157.39   573.8 1188.62   588.7  1195.2   638.4 1221.01   658.4 1229.99
   693.2 1249.62   747.9 1283.28   812.6 1319.48   867.3 1353.68   907.1 1380.97
#Mann= 3 , 0 , 0
       0      .1       0   407.8    .045       0   422.8      .1       0
#XS Ineff= 2 , 0
          406.36 1127.16
Permanent Ineff=
       F       F
Bank Sta=407.8,422.8
XS Rating Curve= 0 ,0
Exp/Cntr=0.3,0.1

Chan Stop Cuts=-1
Use User Specified Reach Order=0